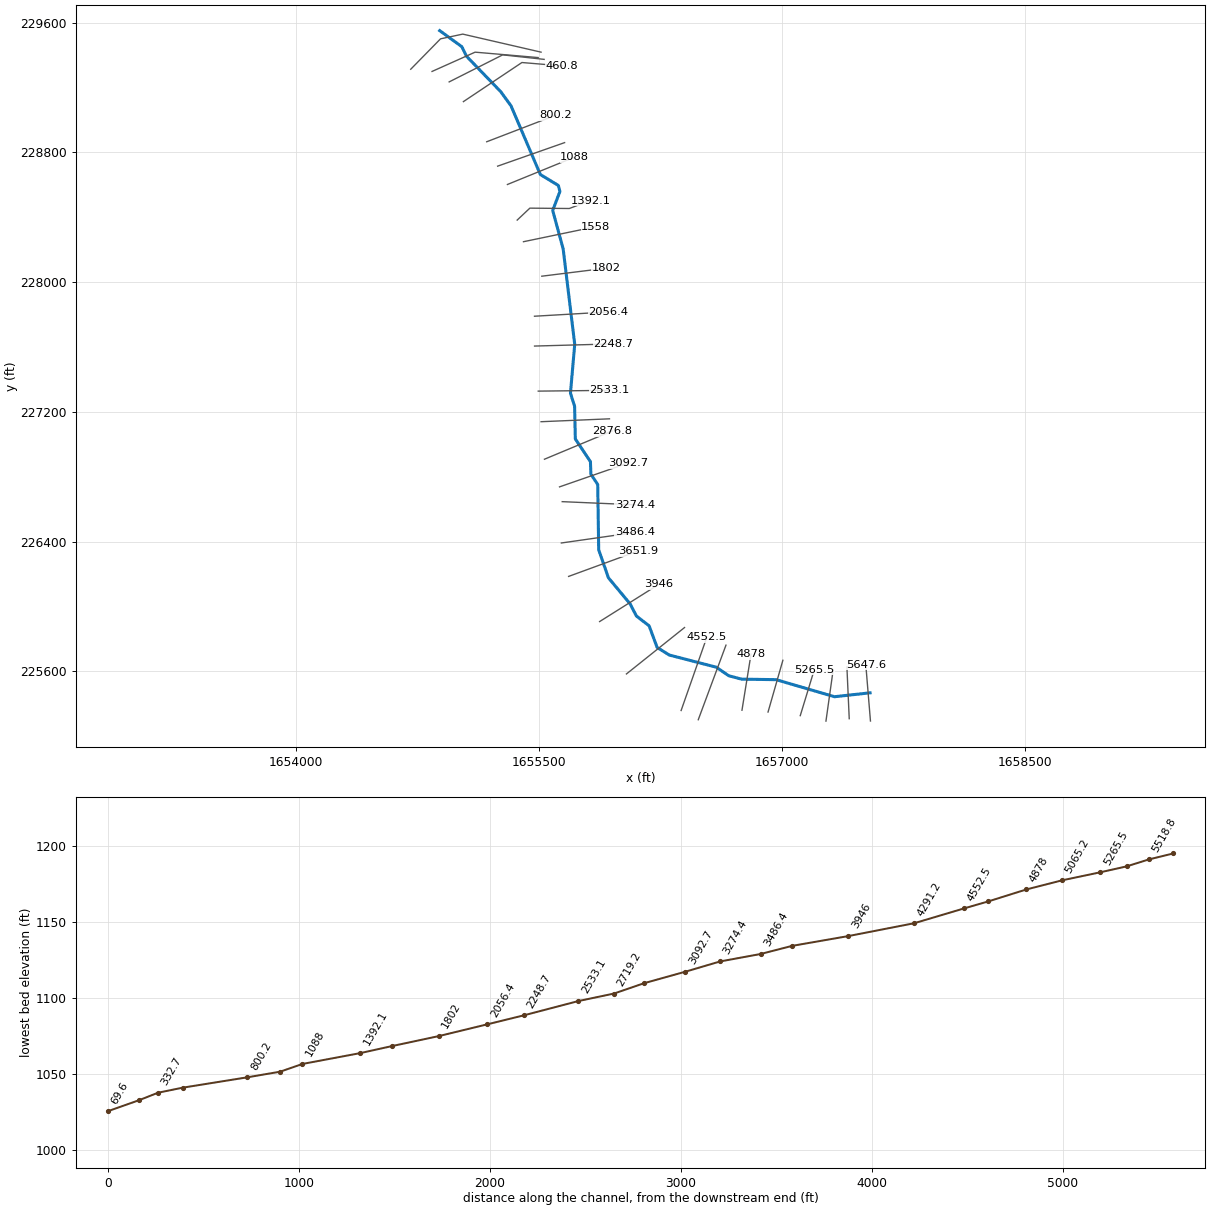
--- np2.prj (project) ---

Proj Title=np2
Current Plan=p01
Default Exp/Contr=0,0
English Units
Geom File=g01
Flow File=f01
Plan File=p01
BEGIN DESCRIPTION:
END DESCRIPTION:
DSS Export Rating Curves= 0
DSS Export Rating Curve Sorted= 0
DSS Export Volume Flow Curves= 0
DXF OffsetX= 0
DXF OffsetY= 0
DXF ScaleX= 0
DXF ScaleY= 0

--- np2.p01 (plan) ---

Plan Title=Approximate Study - 100yr
Program Version=4.00
Geom File=g01
Flow File=f01
Subcritical Flow
K Sum by GR= 0
Std Step Tol= 0.01
Critical Tol= 0.01
Num of Std Step Trials= 20
Max Error Tol= 0.3
Flow Tol Ratio= 0.001
Split Flow NTrial= 30
Split Flow Tol= 0.02
Split Flow Ratio= 0.02
Log Output Level= 0
Friction Slope Method= 1
Unsteady Friction Slope Method= 2
Unsteady Bridges Friction Slope Method= 1
Parabolic Critical Depth
Global Vel Dist= 0 , 0 , 0
Global Log Level= 0
CheckData=True
Encroach Param=-1 ,0,0, 0
Run HTab= 0
Run UNet= 0
Run PostProcess= 0
Run WQNet= 0
UNET Theta= 0
UNET Theta Warmup= 0
UNET ZTol= 0
UNET ZSATol= 0
UNET MxIter= 0
UNET MaxInSteps= 0
UNET DtIC= 0
UNET DtMin= 0
UNET MaxCRTS= 0
UNET WFStab= 0
UNET SFStab= 0
UNET WFX= 1
UNET SFX= 1
UNET DSS MLevel= 1
UNET DZMax Abort= 0
UNET Convert EG Bridges= 0
UNET Use Existing IB Tables= 0
UNET Froude Reduction=False
UNET Froude Limit= 0
UNET Froude Power= 0
UNET Time Slicing=0,0, 5
Write IC File= 0
Echo Input=False
Echo Output=False
Write Detailed= 0
Detailed Automatic Start=False, 0
WQ ULTIMATE=-1
WQ Max Comp Step=1HOUR
WQ Output Interval=15MIN
WQ Output Selected Increments= 0
WQ Output face flow=0
WQ Output face velocity=0
WQ Output face area=0
WQ Output face dispersion=0
WQ Output cell volume=0
WQ Output cell surface area=0
WQ Output cell continuity=0
WQ Output face conc=0
WQ Output face dconc_dx=0
WQ Output face courant=0
WQ Output face peclet=0
WQ Output face adv mass=0
WQ Output face disp mass=0
WQ Output cell mass=0
WQ Output cell source sink temp=0
WQ Output cell source sink nsm=0
WQ Output MaxMinRange=-1
WQ Daily Max Min Mean=-1
WQ Daily Range=0
WQ Daily Time=0
WQ Create Restart=0
WQ Fixed Restart=0
WQ System Summary=False
Sorting and Armoring Iterations= 10
XS Update Threshold= 0.02
Hydraulics Update Threshold= 0.02
Energy Slope Method= 1
Volume Change Method= 0
XS Weighting Method= 0
Number of US Weighted Cross Sections= 1
Number of DS Weighted Cross Sections= 1
Upstream XS Weight=0.25
Main XS Weight=0.5
Downstream XS Weight=0.25
Number of DS XS's Weighted with US Boundary= 1
Upstream Boundary Weight= 1
Weight of XSs Associated with US Boundary= 0
Number of US XS's Weighted with DS Boundary= 1
Downstream Boundary Weight= 0.5
Weight of XSs Associated with DS Boundary= 0.5
Sediment Output Level= 4
Mass or Volume Output= 0
Output Increment Type= 1
Profile and TS Output Increment= 10
XS Output Flag= 0
XS Output Increment= 10
Disregard all LS=0
Disregard all Conn=0
Disregard all Breaches=0
Disregard all Pumps=0

--- np2.f01 (steady flow) ---

Flow Title=USGS Regression Equation
Program Version=4.00
Number of Profiles= 1
Profile Names=P100yr
River Rch & RM=np2,Main            ,5647.6
     363
River Rch & RM=np2,Main            ,5265.5
     371
River Rch & RM=np2,Main            ,3651.9
     410
River Rch & RM=np2,Main            ,2533.1
     455
River Rch & RM=np2,Main            ,460.8
     486
River Rch & RM=np2,Main            ,69.6
    1131
Boundary for River Rch & Prof#=np2,Main            , 1
Up Type= 0
Dn Type= 3
Dn Slope=0.014871
DSS Import GetInterval= 0
DSS Import GetPeak= 0
DSS Import FillOption= 0

--- np2.g01 (geometry) ---

Geom Title=USGS 3m DEM
Program Version=4.00

River Reach=np2             ,Main
Reach XY= 30
     1657542.281      225468.378     1657322.985      225444.377
      1656962.52      225549.571     1656750.738      225552.606
     1656671.135      225573.645     1656594.541      225626.227
     1656304.666      225701.369     1656229.572      225747.942
     1656180.026      225881.628      1656101.93       225941.72
      1656062.89      226016.825     1655929.235      226177.559
      1655869.18      226350.298     1655863.231      226752.835
     1655821.184      226815.925     1655818.192       226894.03
     1655725.088      227033.729     1655720.611      227234.998
     1655695.089      227316.109     1655721.454      227617.097
     1655650.159        228205.3     1655585.607      228442.625
     1655630.206      228559.358      1655620.32      228596.785
      1655509.45      228663.872     1655328.859       229087.02
     1655265.787      229174.145     1655054.038      229393.467
     1655025.508      229452.049     1654888.841      229551.201

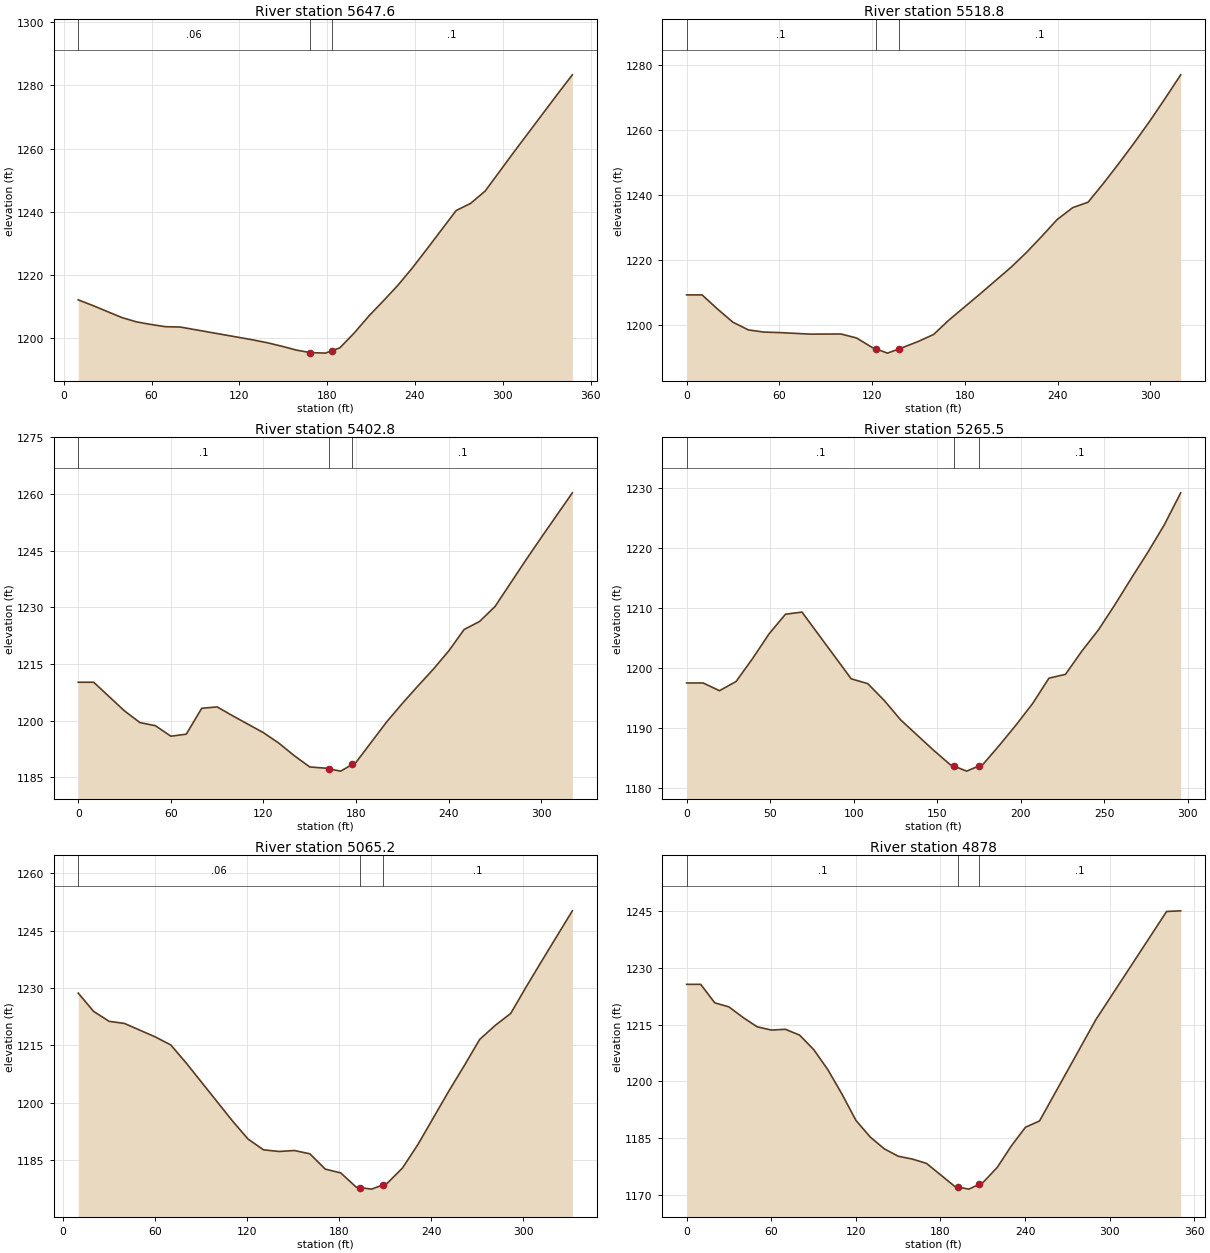
Type RM Length L Ch R = 1 ,5647.6  ,129.7,128.8,127.9
XS GIS Cut Line= 2
     1657544.834      225294.585     1657516.097      225641.035
#Sta/Elev= 27
     9.9 1212.07    19.9 1210.27    39.7 1206.47    49.7  1205.1    59.6 1204.28
    69.5 1203.57    79.5 1203.47   129.1 1199.41   139.1 1198.49     149 1197.39
   158.9 1196.17   168.3 1195.38   178.8  1195.2   183.31195.962   188.7 1196.88
   198.7 1201.67   208.6 1206.99   218.5 1211.78   228.4  1216.7   238.4 1222.28
   248.3 1228.22   268.2 1240.37   278.1 1242.63     288 1246.53   307.9 1259.03
   337.7 1277.38   347.6 1283.34
#Mann= 3 , 0 , 0
     9.9     .06       0   168.3    .045       0   183.3      .1       0
Bank Sta=168.3,183.3
XS Rating Curve= 0 ,0
Exp/Cntr=0.3,0.1

Type RM Length L Ch R = 1 ,5518.8  ,120.2,116.1,111.9
XS GIS Cut Line= 2
     1657413.918      225308.954     1657399.549      225628.263
#Sta/Elev= 30
       0 1209.15      10 1209.15      20  1204.8      30 1200.73      40 1198.37
    49.9 1197.71    59.9 1197.56    79.9 1197.08    99.9 1197.11   109.9  1195.9
   119.9 1193.01   122.4 1192.56   129.9 1191.23   137.4 1192.51   149.8 1194.81
   159.8 1196.98   169.8 1201.45   189.8 1209.44   209.8 1217.63   219.7 1222.14
   229.7 1227.15   239.7 1232.34   249.7 1235.99   259.7 1237.68   269.7 1243.52
   279.7 1249.68   289.7 1256.05   299.7 1262.69   309.6 1269.66   319.6 1276.87
#Mann= 3 , 0 , 0
       0      .1       0   122.4    .045       0   137.4      .1       0
Bank Sta=122.4,137.4
XS Rating Curve= 0 ,0
Exp/Cntr=0.3,0.1

Type RM Length L Ch R = 1 ,5402.8  ,140.8,137.3,133.8
XS GIS Cut Line= 2
     1657270.418       225294.19     1657315.056      225611.115
#Sta/Elev= 30
       0 1210.19      10 1210.19      30 1202.59      40 1199.51      50 1198.69
      60 1195.91      70 1196.45      80  1203.3      90 1203.66     100 1201.32
     120 1196.84     130 1194.06     140 1190.74     150 1187.77     160 1187.46
   162.5 1187.26     170 1186.67   177.5 1188.43     180 1189.02     200  1199.8
     210  1204.6     220 1209.18     230 1213.63     240 1218.46     250 1224.15
     260 1226.27     270 1230.23     290 1242.53     300 1248.51   320.1 1260.31
#Mann= 3 , 0 , 0
       0      .1       0   162.5    .045       0   177.5      .1       0
Bank Sta=162.5,177.5
XS Rating Curve= 0 ,0
Exp/Cntr=0.3,0.1

Type RM Length L Ch R = 1 ,5265.5  ,199.8,200.2,200.6
XS GIS Cut Line= 2
     1657111.956      225327.668     1657198.384      225610.701
#Sta/Elev= 30
       0  1197.5     9.9  1197.5    19.7 1196.21    29.6 1197.74    39.5 1201.57
    49.3 1205.66    59.2 1208.97    69.1 1209.33    98.6 1198.19   108.5 1197.39
   118.4 1194.57   128.2 1191.34     148 1186.25   157.8 1183.89   160.2 1183.62
   167.7 1182.79   175.2 1183.67   177.6 1183.95   187.4 1187.13   197.3 1190.49
   207.2 1194.06     217  1198.3   226.9 1198.94   236.7 1202.82   246.6 1206.35
   256.5 1210.56   266.3 1214.96   276.2  1219.3   286.1  1223.9   295.9 1229.23
#Mann= 3 , 0 , 0
       0      .1       0   160.2    .045       0   175.2      .1       0
Bank Sta=160.2,175.2
XS Rating Curve= 0 ,0
Exp/Cntr=0.3,0.1

Type RM Length L Ch R = 1 ,5065.2  ,184.4,187.2,190
XS GIS Cut Line= 2
      1656913.32      225349.987     1657004.826      225669.144
#Sta/Elev= 30
    10.1 1228.68    20.1 1223.91    30.2 1221.31    40.2 1220.76    60.4 1217.22
    70.4 1215.14    80.5  1210.4   110.7 1195.24   120.7 1190.58   130.8 1187.76
   140.9 1187.33   150.9 1187.58     161 1186.72     171 1182.73   181.1 1181.73
   191.2 1178.02   193.7 1177.89   201.2  1177.5   208.7 1178.61   211.3 1178.99
   221.3    1183   231.4 1189.16   251.5 1203.08   261.6 1209.75   271.6 1216.57
   281.7 1220.23   291.8 1223.35   301.8 1230.22   311.9 1236.96     332 1250.16
#Mann= 3 , 0 , 0
    10.1     .06       0   193.7    .045       0   208.7      .1       0
Bank Sta=193.7,208.7
XS Rating Curve= 0 ,0
Exp/Cntr=0.3,0.1

Type RM Length L Ch R = 1 ,4878    ,203.6,199.2,194.9
XS GIS Cut Line= 2
     1656752.625      225361.146     1656808.422      225707.086
#Sta/Elev= 30
       0  1225.7      10  1225.7      20  1220.8      30 1219.74      40 1216.94
    50.1 1214.45    60.1  1213.6    70.1  1213.8    80.1 1212.27    90.1 1208.45
   100.1 1203.15   110.1 1196.71   120.1 1189.68   130.2 1185.29   140.2 1182.15
   150.2 1180.18   160.2 1179.44   170.2 1178.29   190.2  1172.2   192.7 1172.02
   200.2 1171.49   207.7 1172.81   210.2 1173.25   220.3 1177.24   230.3 1182.93
   240.3 1187.87   250.3 1189.54   290.3  1216.4   340.4 1244.99   350.4 1245.16
#Mann= 3 , 0 , 0
       0      .1       0   192.7    .045       0   207.7      .1       0
Bank Sta=192.7,207.7
XS Rating Curve= 0 ,0
Exp/Cntr=0.3,0.1

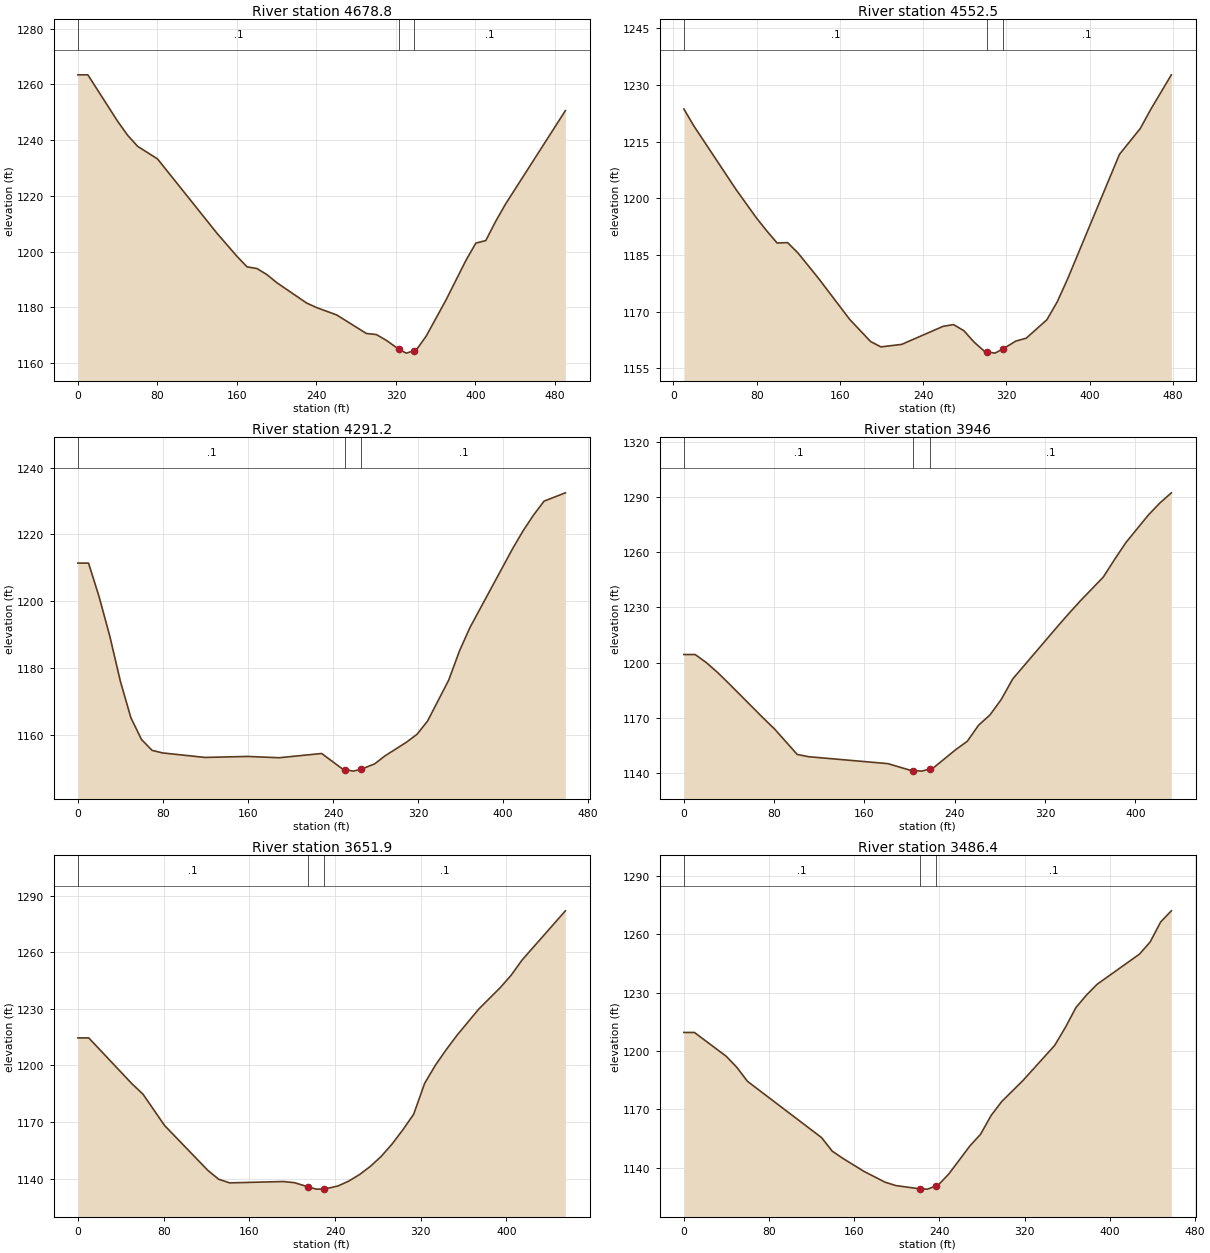
Type RM Length L Ch R = 1 ,4678.8  ,125.9,126.3,126.7
XS GIS Cut Line= 2
     1656483.132      225302.568     1656653.962      225762.373
#Sta/Elev= 30
       0 1263.42      10 1263.42      40 1246.75    50.1 1241.72    60.1 1237.78
    80.1 1233.27   140.1 1206.54   160.2 1198.28   170.2 1194.57   180.2 1193.96
   190.2 1191.78   200.2 1188.87   230.2 1181.58   240.3 1179.94   260.3 1177.34
   290.3 1170.67   300.3  1170.3   310.3 1168.22   322.8 1165.06   330.3 1163.63
   337.8 1164.43   340.4  1164.7   350.4  1169.7   370.4 1182.71   390.4 1196.87
   400.4 1203.08   410.4 1203.99   420.4 1210.91   430.5 1217.21   490.5 1250.58
#Mann= 3 , 0 , 0
       0      .1       0   322.8    .045       0   337.8      .1       0
Bank Sta=322.8,337.8
XS Rating Curve= 0 ,0
Exp/Cntr=0.3,0.1

Type RM Length L Ch R = 1 ,4552.5  ,274.2,261.3,248.4
XS GIS Cut Line= 2
      1656377.42      225359.323     1656535.815      225811.036
#Sta/Elev= 30
      10 1223.61    19.9 1219.01    59.8 1202.47    79.8 1194.79    89.8 1191.34
    99.7 1188.16   109.7 1188.28   119.7 1185.54   139.6 1178.77   169.5 1167.94
   189.5 1162.12   199.4 1160.69   219.4 1161.35   259.3 1166.13   269.3 1166.59
   279.2 1164.97   289.2 1161.91   299.2 1159.48   301.6 1159.38   309.1 1159.04
   316.6 1160.11   329.1 1162.22   339.1 1162.98     359 1167.86     369 1172.62
     379  1178.7   428.8 1211.62   448.8 1218.45   458.7 1223.43   478.7 1232.66
#Mann= 3 , 0 , 0
      10      .1       0   301.6    .045       0   316.6      .1       0
#XS Ineff= 2 , 0
       0   269.3 1166.59               0
Permanent Ineff=
       F       F
Bank Sta=301.6,316.6
XS Rating Curve= 0 ,0
Exp/Cntr=0.3,0.1

Type RM Length L Ch R = 1 ,4291.2  ,347.6,345.1,342.7
XS GIS Cut Line= 2
      1656040.23      225584.735     1656398.515      225870.938
#Sta/Elev= 30
       0 1211.44      10 1211.44    19.9 1201.42    29.9 1189.74    39.9  1176.2
    49.8 1165.27    59.8 1158.74    69.8 1155.48    79.8 1154.71   119.6 1153.37
   159.5 1153.67   189.4 1153.28   229.3 1154.55   249.2 1149.87   251.7 1149.72
   259.2 1149.28   266.7 1149.88   279.1 1151.44   289.1 1153.88     309  1157.9
     319 1160.28     329 1164.27   348.9 1176.52   358.9 1185.14   368.8 1192.18
   408.7 1215.61   418.7 1221.03   428.7 1225.83   438.6 1229.97   458.6 1232.44
#Mann= 3 , 0 , 0
       0      .1       0   251.7    .045       0   266.7      .1       0
Bank Sta=251.7,266.7
XS Rating Curve= 0 ,0
Exp/Cntr=0.3,0.1

Type RM Length L Ch R = 1 ,3946    ,298.9,294.2,289.5
XS GIS Cut Line= 2
     1655874.848      225907.658     1656240.457      226137.561
#Sta/Elev= 30
       0 1204.36      10 1204.36    20.1 1199.85    30.1 1194.44    40.2 1188.36
    70.3 1169.76    80.4 1163.74   100.4  1149.9   110.5 1148.67   180.8 1144.89
   200.9 1141.23   203.4 1141.12   210.9 1140.81   218.4 1142.11     221 1142.56
   241.1 1152.63   251.1 1157.07   261.1 1165.83   271.2 1171.43   281.2 1179.87
   291.3    1191   331.4 1219.89   341.5 1226.99   351.5 1233.74   371.6 1246.56
   381.7 1256.25   391.7 1265.43   411.8 1280.56   421.8 1286.97   431.9 1292.47
#Mann= 3 , 0 , 0
       0      .1       0   203.4    .045       0   218.4      .1       0
Bank Sta=203.4,218.4
XS Rating Curve= 0 ,0
Exp/Cntr=0.3,0.1

Type RM Length L Ch R = 1 ,3651.9  ,170.2,165.5,160.8
XS GIS Cut Line= 2
     1655683.828      226186.152     1656111.105      226342.548
#Sta/Elev= 30
       0 1214.62    10.1 1214.62    50.6 1190.19    60.7 1184.79    80.9 1168.13
   121.3 1144.31   131.4 1139.61   141.6 1137.69   192.1  1138.4   202.2 1137.78
   214.9 1135.56   222.4 1134.37   229.9 1134.38   242.7 1136.04   252.8 1138.64
   262.9 1142.11     273 1146.46   283.1 1151.74   293.2 1158.28   303.3 1165.85
   313.4 1174.13   323.6 1190.46   333.7 1200.16   343.8 1208.41   353.9 1216.06
   374.1 1229.88   394.3 1241.35   404.4 1247.89   414.6 1255.96     455 1282.05
#Mann= 3 , 0 , 0
       0      .1       0   214.9    .045       0   229.9      .1       0
Bank Sta=214.9,229.9
XS Rating Curve= 0 ,0
Exp/Cntr=0.3,0.1

Type RM Length L Ch R = 1 ,3486.4  ,216.1,212,207.8
XS GIS Cut Line= 2
     1655638.924      226392.269     1656091.993      226456.993
#Sta/Elev= 30
       0 1209.59     9.9 1209.59    39.8 1197.31    49.7 1191.66    59.7 1184.46
   129.3  1155.5   139.3 1148.54   149.2 1144.86   169.1 1138.13     189 1132.56
     199 1130.84   221.3 1129.17   228.8 1129.01   236.3 1130.58   238.8  1131.1
   248.7 1136.78   268.6 1151.26   278.6 1157.25   288.5 1166.91   298.5  1174.1
   318.4 1184.88   348.2 1202.95   358.2 1212.18   368.1 1222.39   378.1 1228.86
     388 1234.35   427.8 1249.88   437.8 1256.11   447.7 1266.44   457.7 1272.13
#Mann= 3 , 0 , 0
       0      .1       0   221.3    .045       0   236.3      .1       0
Bank Sta=221.3,236.3
XS Rating Curve= 0 ,0
Exp/Cntr=0.3,0.1

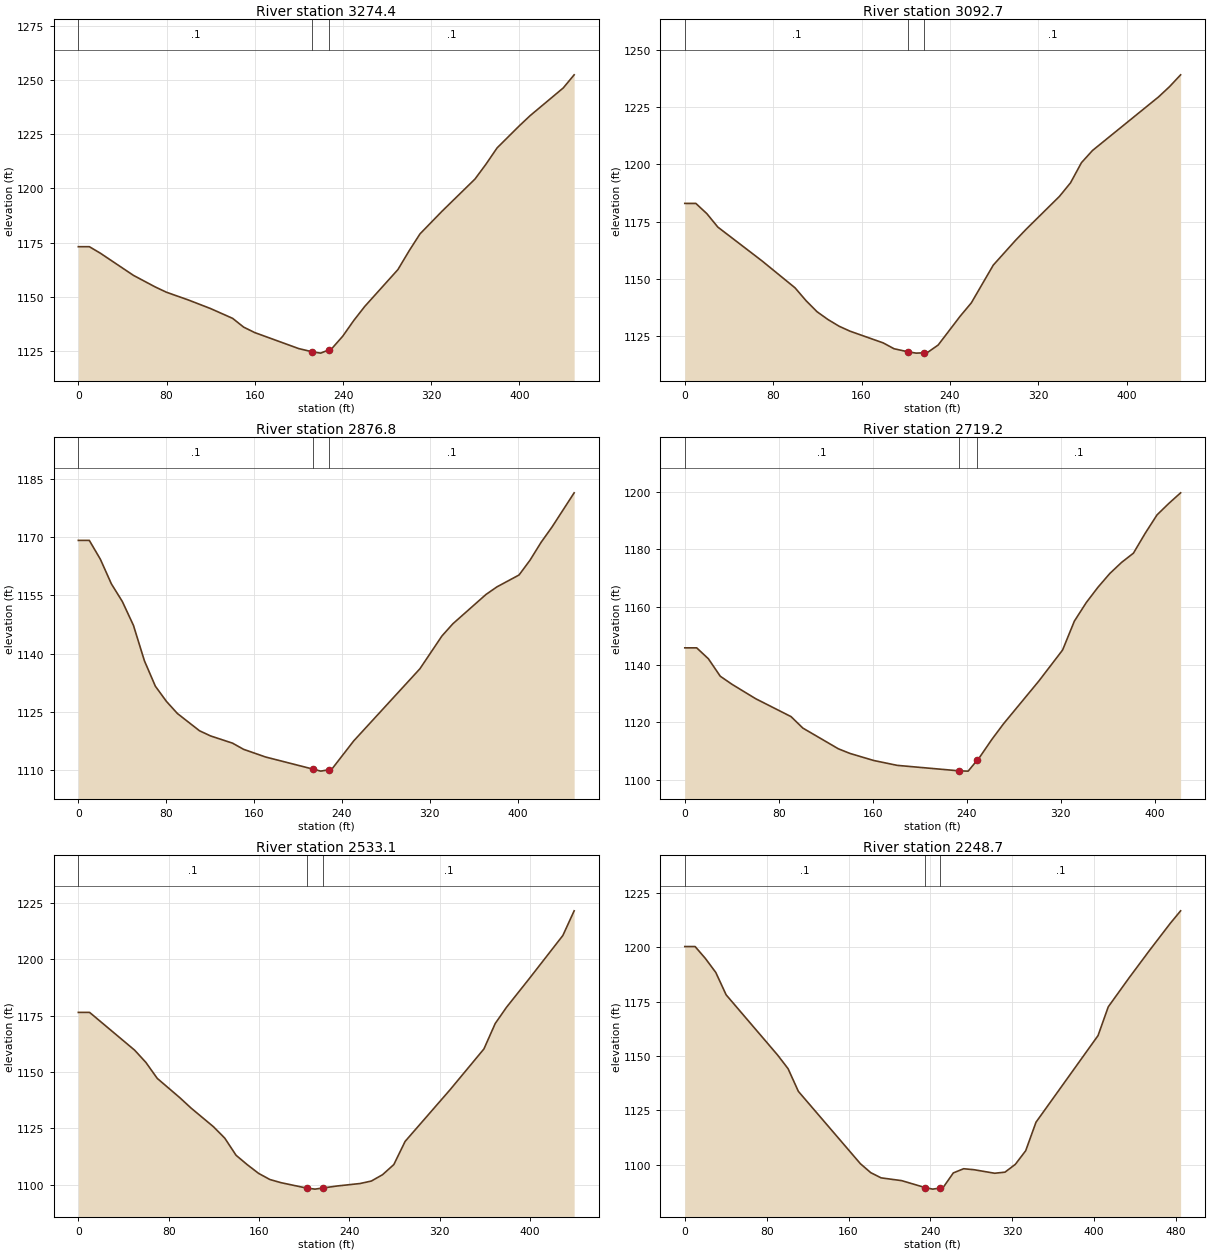
Type RM Length L Ch R = 1 ,3274.4  ,173.2,181.7,190.3
XS GIS Cut Line= 2
     1655644.345      226647.042     1656093.575        226627.7
#Sta/Elev= 30
       0 1173.16      10 1173.16      20 1170.15      50 1159.94    69.9 1154.56
    79.9 1152.17    99.9 1148.58   119.9 1144.64   139.9 1140.13   149.9 1136.09
   159.9 1133.58   199.8  1126.2   212.3 1124.68   219.8  1124.1   227.3 1125.64
   229.8 1126.16   239.8 1131.93   249.8 1139.17   259.8 1145.67   289.8 1162.61
   299.8 1171.13   309.8 1179.05   329.7 1189.46   359.7 1204.35   369.7 1211.23
   379.7 1218.68   399.7 1228.79   409.7 1233.57   439.7 1246.33   449.6 1252.38
#Mann= 3 , 0 , 0
       0      .1       0   212.3    .045       0   227.3      .1       0
Bank Sta=212.3,227.3
XS Rating Curve= 0 ,0
Exp/Cntr=0.3,0.1

Type RM Length L Ch R = 1 ,3092.7  ,214.7,215.8,216.9
XS GIS Cut Line= 2
     1655627.765      226738.208      1656051.82      226885.511
#Sta/Elev= 30
       0 1182.92      10 1182.92      20 1178.42    29.9 1172.56    69.8 1157.79
    99.8 1145.96   109.7 1140.37   119.7  1135.5   129.7 1132.05   139.7 1129.14
   149.6 1126.97   179.6 1121.84   189.5 1119.27     202 1117.95   209.5 1117.36
     217 1117.51   219.5 1117.56   229.4 1120.91   249.4 1133.58   259.4 1139.36
   279.3 1155.91   299.3 1166.68   309.2 1171.69   339.2    1186   349.2 1191.93
   359.1 1200.75   369.1 1206.09     429 1229.59   438.9 1234.07   448.9 1239.23
#Mann= 3 , 0 , 0
       0      .1       0     202    .045       0     217      .1       0
Bank Sta=202,217
XS Rating Curve= 0 ,0
Exp/Cntr=0.3,0.1

Type RM Length L Ch R = 1 ,2876.8  ,165.4,157.6,149.8
XS GIS Cut Line= 2
     1655534.784      226908.692     1655951.482      227082.716
#Sta/Elev= 30
       0 1169.16      10 1169.16    20.1  1164.3    30.1 1157.98    40.1 1153.43
    50.2  1147.3    60.2 1138.18    70.2 1131.63    80.3 1127.72    90.3 1124.61
   110.4 1120.18   120.4 1118.86   140.5 1116.99   150.5 1115.41   170.6 1113.43
   213.3 1110.35   220.8  1109.8   228.3 1110.16   230.8 1110.28   250.9  1117.6
   311.1 1136.13   331.2 1144.58   341.2 1147.73   371.3 1155.25   381.3 1157.21
   401.4 1160.26   411.4 1164.07   421.5 1168.67   431.5 1172.63   451.6  1181.4
#Mann= 3 , 0 , 0
       0      .1       0   213.3    .045       0   228.3      .1       0
Bank Sta=213.3,228.3
XS Rating Curve= 0 ,0
Exp/Cntr=0.3,0.1

Type RM Length L Ch R = 1 ,2719.2  ,186.9,186.1,185.3
XS GIS Cut Line= 2
      1655513.94      227139.944     1655935.763      227157.799
#Sta/Elev= 30
       0 1145.82    10.1 1145.82    20.1 1142.02    30.2 1135.96    40.2 1133.15
    60.3 1128.16    90.5 1121.92   100.5 1117.95   130.7 1110.76   140.7 1109.13
   160.8 1106.69   180.9 1104.99   233.8 1103.08   241.3 1102.99   248.8 1106.71
   251.3 1107.95   261.4 1113.97   271.4 1119.43   301.6 1134.35   321.7 1145.06
   331.7 1155.08   341.8 1161.51   351.8 1166.86   361.9 1171.64   371.9 1175.49
     382  1178.7     392 1185.59   402.1    1192   412.1 1195.97   422.2 1199.67
#Mann= 3 , 0 , 0
       0      .1       0   233.8    .045       0   248.8      .1       0
Bank Sta=233.8,248.8
XS Rating Curve= 0 ,0
Exp/Cntr=0.3,0.1

Type RM Length L Ch R = 1 ,2533.1  ,284.1,284.4,284.8
XS GIS Cut Line= 2
     1655496.467      227328.584     1655935.517      227333.373
#Sta/Elev= 30
       0 1176.49      10 1176.49    49.9 1159.72    59.9 1154.25    69.9  1147.2
    89.8 1138.68    99.8 1134.05   119.7 1125.74   129.7 1120.68   139.7 1113.08
   149.7 1108.87   159.7 1105.03   169.6 1102.33   179.6 1100.91   202.1 1098.53
   209.6 1098.06   217.1  1098.6   229.5 1099.47   249.5 1100.55   259.5 1101.65
   269.4 1104.46   279.4 1108.96   289.4 1119.24   329.3 1142.22   359.2 1160.28
   369.2 1171.57   379.2 1178.77   399.2 1191.38   429.1 1210.63   439.1 1221.57
#Mann= 3 , 0 , 0
       0      .1       0   202.1    .045       0   217.1      .1       0
Bank Sta=202.1,217.1
XS Rating Curve= 0 ,0
Exp/Cntr=0.3,0.1

Type RM Length L Ch R = 1 ,2248.7  ,191.6,192.3,193
XS GIS Cut Line= 2
     1655473.766      227606.404     1655958.081      227619.795
#Sta/Elev= 30
       0 1200.41    10.1 1200.41    20.2 1194.88    30.3 1188.48    40.4 1178.18
    90.8 1150.39   100.9 1144.18     111 1133.71   171.6  1100.4   181.7 1096.29
   191.8 1093.89     212  1092.6   234.8 1089.42   242.2  1088.7   249.8 1089.19
   252.3 1089.35   262.4 1096.17   272.5 1098.09   282.6 1097.64   302.8 1096.01
   312.9 1096.52     323 1100.13   333.1 1106.38   343.2 1119.53   403.8 1159.41
   413.8 1172.66     434 1185.91   454.2  1198.7   474.4 1211.12   484.5 1216.87
#Mann= 3 , 0 , 0
       0      .1       0   234.8    .045       0   249.8      .1       0
Bank Sta=234.8,249.8
XS Rating Curve= 0 ,0
Exp/Cntr=0.3,0.1

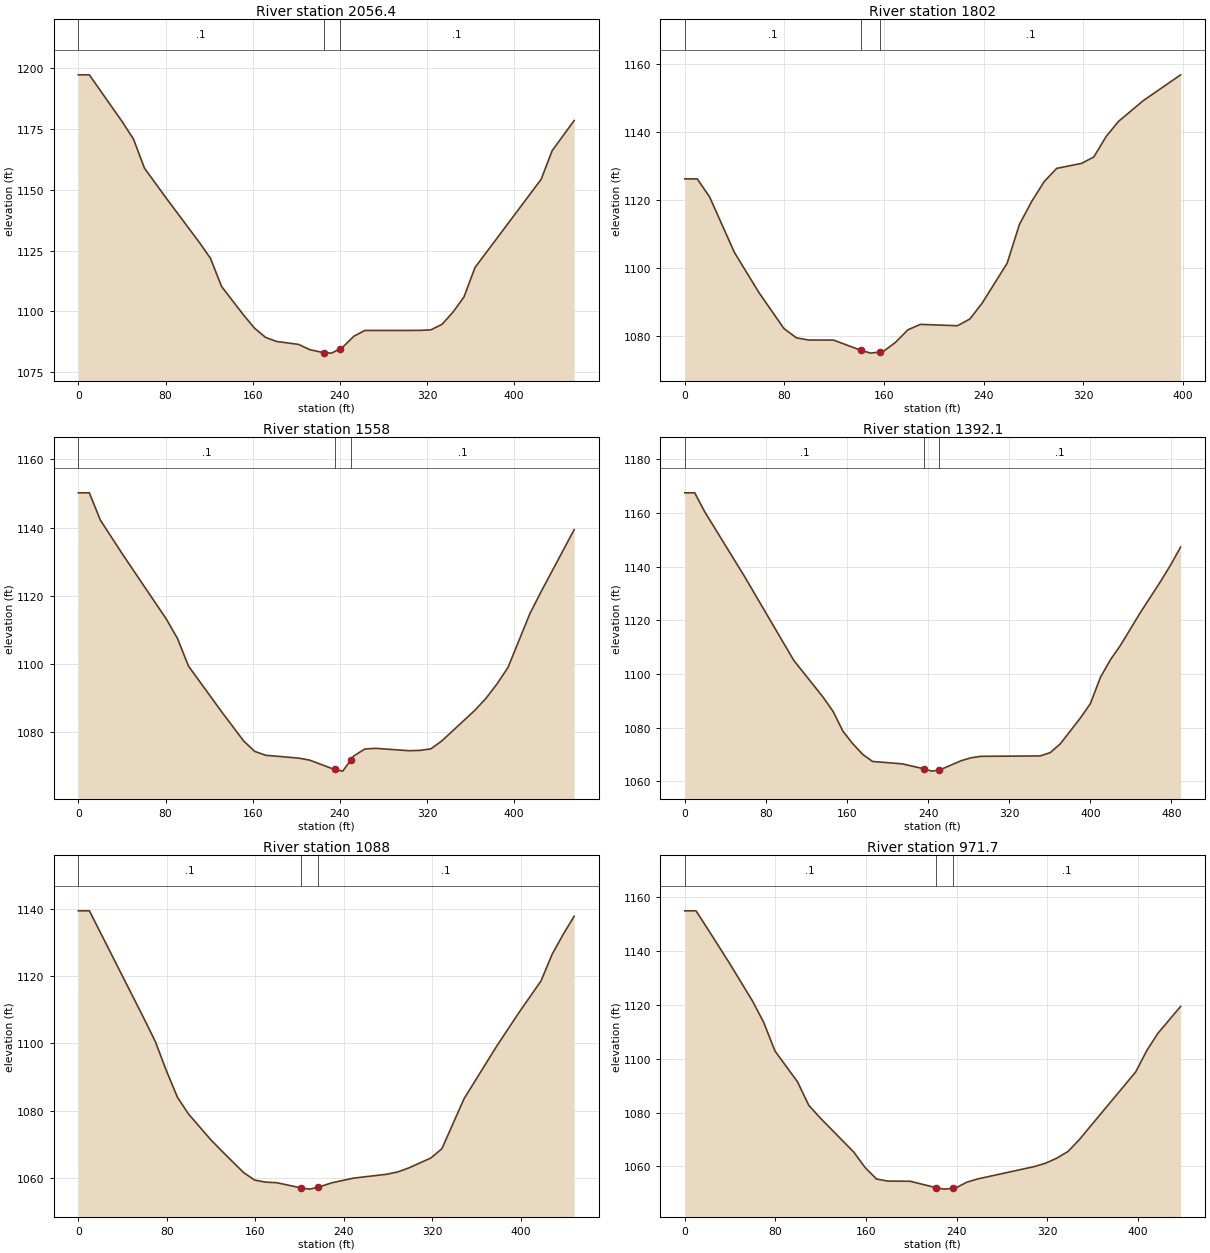
Type RM Length L Ch R = 1 ,2056.4  ,252.9,254.4,255.8
XS GIS Cut Line= 2
     1655473.368      227790.332       1655927.6      227816.762
#Sta/Elev= 30
       0 1197.39    10.1 1197.39    40.4    1178    50.6 1170.93    60.7 1158.93
    80.9 1146.47   111.2 1128.27   121.3 1121.78   131.4 1110.25   151.7 1098.41
   161.8 1092.98   171.9 1089.21     182 1087.55   202.2 1086.34   212.3 1084.19
   225.1 1082.94   232.6 1082.75   240.1  1084.6   242.7 1085.24   252.8 1089.69
   262.9 1092.09   313.4 1092.11   323.6 1092.35   333.7 1094.59   343.8 1099.64
   353.9 1105.89     364    1118   424.7 1154.34   434.8 1166.13     455 1178.57
#Mann= 3 , 0 , 0
       0      .1       0   225.1    .045       0   240.1      .1       0
Bank Sta=225.1,240.1
XS Rating Curve= 0 ,0
Exp/Cntr=0.3,0.1

Type RM Length L Ch R = 1 ,1802    ,242.2,244,245.9
XS GIS Cut Line= 2
     1655518.404      228037.154     1655913.444      228086.255
#Sta/Elev= 30
       0 1126.25      10 1126.25    19.9 1120.96    39.8 1104.64    59.7 1092.71
    79.6 1082.23    89.6 1079.49    99.5 1078.84   119.4 1078.83   141.8 1075.77
   149.3 1074.99   156.8 1075.33   159.2 1075.43   169.2 1078.16   179.1 1081.84
   189.1 1083.45   218.9 1083.05   228.9 1085.03   238.8 1089.73   258.8 1101.42
   268.7 1112.87   278.7 1119.72   288.6 1125.47   298.6 1129.34   318.5  1130.8
   328.4  1132.7   338.4 1138.78   348.3 1143.18   368.2 1149.29   398.1 1156.86
#Mann= 3 , 0 , 0
       0      .1       0   141.8    .045       0   156.8      .1       0
Bank Sta=141.8,156.8
XS Rating Curve= 0 ,0
Exp/Cntr=0.3,0.1

Type RM Length L Ch R = 1 ,1558    ,170.9,165.9,160.9
XS GIS Cut Line= 2
     1655405.464       228249.79       1655850.9       228342.39
#Sta/Elev= 30
       0  1150.2    10.1  1150.2    20.2  1142.2    40.4 1132.25    80.9 1113.05
      91 1107.41   101.1 1099.31   131.4 1085.93   151.7 1077.33   161.8 1074.26
   171.9 1073.11   202.2 1072.27   212.3 1071.68   235.1 1068.93   242.6 1068.45
   250.1 1071.73   252.8 1072.91   262.9 1074.95     273 1075.14   303.3 1074.45
   313.4 1074.54   323.5 1074.99   333.6 1077.34     364 1086.35   374.1 1089.84
   384.2 1094.05   394.3 1098.91   414.5  1114.8   424.6 1121.12     455 1139.38
#Mann= 3 , 0 , 0
       0      .1       0   235.1    .045       0   250.1      .1       0
Bank Sta=235.1,250.1
XS Rating Curve= 0 ,0
Exp/Cntr=0.3,0.1

Type RM Length L Ch R = 1 ,1392.1  ,294,304.1,314.2
XS GIS Cut Line= 4
     1655366.637      228383.093     1655444.752      228456.744
     1655688.026      228454.513     1655817.474      228503.614
#Sta/Elev= 30
       0 1167.56     9.8 1167.56    19.5 1160.59    58.6 1136.59   107.4 1105.17
   136.6  1091.3   146.3 1086.08     156  1078.7   165.7 1074.04   175.5 1070.07
   185.2 1067.43   214.4 1066.55   236.1 1064.68   243.6 1063.83   251.1 1064.21
   272.8 1067.74   282.5 1068.81   292.3 1069.35   350.6 1069.49   360.5 1070.74
   370.4    1074   390.2 1083.62   400.1 1088.99     410 1098.79   419.9 1105.36
   429.8 1110.74   449.5    1123   469.3 1134.51   479.2 1140.64   489.1 1147.36
#Mann= 3 , 0 , 0
       0      .1       0   236.1    .045       0   251.1      .1       0
Bank Sta=236.1,251.1
XS Rating Curve= 0 ,0
Exp/Cntr=0.3,0.1

Type RM Length L Ch R = 1 ,1088    ,117.5,116.4,115.2
XS GIS Cut Line= 2
     1655306.478      228602.626      1655721.58       228771.86
#Sta/Elev= 30
       0 1139.37      10 1139.37    59.8 1107.08    69.7 1100.45    79.7 1091.78
    89.7  1083.9    99.6    1079   119.5 1071.42   129.5 1068.06   149.4 1061.58
   159.4 1059.35   169.3 1058.73   179.3 1058.56   201.7    1057   209.2 1056.65
   216.7 1057.19   229.1 1058.52     249 1059.93   278.9 1061.07   288.9 1061.77
   298.8 1062.95   318.8 1065.91   328.7 1068.66   348.7 1083.49   378.5 1099.27
   398.5 1109.18   418.4 1118.56   428.4 1126.45   438.3 1132.33   448.3 1137.75
#Mann= 3 , 0 , 0
       0      .1       0   201.7    .045       0   216.7      .1       0
Bank Sta=201.7,216.7
XS Rating Curve= 0 ,0
Exp/Cntr=0.3,0.1

Type RM Length L Ch R = 1 ,971.7   ,170.8,171.5,172.2
XS GIS Cut Line= 2
     1655246.116      228715.641     1655659.011      228860.712
#Sta/Elev= 30
       0 1154.84     9.9 1154.84    19.9 1148.33    39.8 1135.17    59.7 1121.41
    69.6 1113.49    79.6 1102.82    99.5 1091.38   109.4 1082.68   119.4 1078.05
   149.2 1065.28   159.1 1059.61   169.1 1055.35     179 1054.55   198.9 1054.49
   221.3 1052.16   228.8 1051.57   236.3 1051.82   238.7  1051.9   248.7  1054.1
   258.6 1055.36   308.3 1059.92   318.3 1061.17   328.2 1063.03   338.2 1065.54
   348.1  1069.9   397.9 1095.03   407.8 1103.03   417.7 1109.46   437.6 1119.38
#Mann= 3 , 0 , 0
       0      .1       0   221.3    .045       0   236.3      .1       0
Bank Sta=221.3,236.3
XS Rating Curve= 0 ,0
Exp/Cntr=0.3,0.1

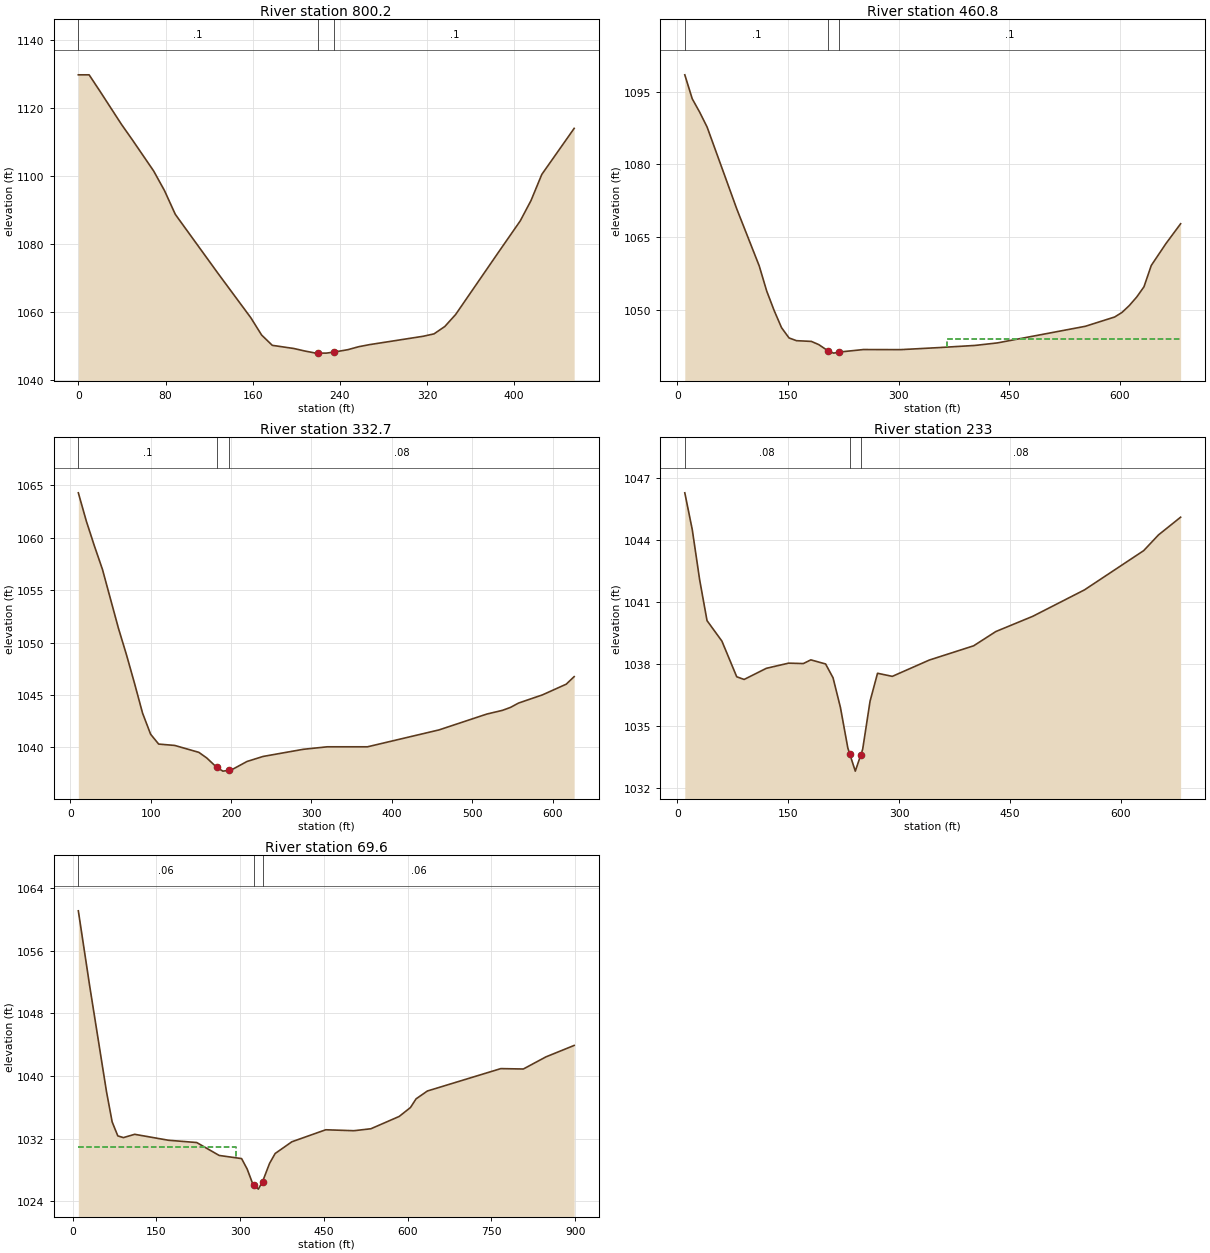
Type RM Length L Ch R = 1 ,800.2   ,334.4,339.4,344.3
XS GIS Cut Line= 3
     1655178.747      228866.036     1655391.095      228947.673
     1655603.443      229029.311
#Sta/Elev= 30
       0 1129.71     9.9 1129.71    19.8 1124.92    39.6 1115.14    49.5 1110.63
    69.2  1101.4    79.1 1095.65      89 1088.68   128.6 1071.15   158.3 1058.28
   168.2  1053.2     178 1050.17   197.8 1049.24   207.7 1048.51   217.6  1047.9
     220  1047.9   227.5 1047.88     235 1048.21   247.3 1048.89   257.2 1049.76
   267.1 1050.37   316.5 1052.84   326.4 1053.54   336.3 1055.71   346.2 1059.22
   385.8 1077.66   405.5 1086.75   415.4 1092.74   425.3 1100.42     455 1113.96
#Mann= 3 , 0 , 0
       0      .1       0     220    .045       0     235      .1       0
Bank Sta=220,235
XS Rating Curve= 0 ,0
Exp/Cntr=0.3,0.1

Type RM Length L Ch R = 1 ,460.8   ,131.3,128.1,125
XS GIS Cut Line= 3
     1655035.065      229113.521     1655395.884      229354.599
     1655643.349      229333.844
#Sta/Elev= 30
    10.1  1098.5    20.2 1093.55    30.3 1090.78    40.4  1087.7    80.7 1070.76
     111 1059.05   121.1 1053.88   131.2 1049.85   141.3 1046.28   151.4 1044.18
   161.5 1043.61   181.7 1043.46   191.7  1042.8   204.4  1041.5   211.9 1041.04
   219.4 1041.26   252.3 1041.78   302.8 1041.76   353.2 1042.17   403.7 1042.63
   433.9 1043.15   553.1 1046.58   592.9  1048.5   602.8 1049.44   612.7 1050.86
   622.7 1052.61   632.6 1054.73   642.5 1059.14   662.4 1063.66   682.3 1067.75
#Mann= 3 , 0 , 0
    10.1      .1       0   204.4    .045       0   219.4      .1       0
#XS Ineff= 2 , 0
       0                     365       0    1044
Permanent Ineff=
       F       F
Bank Sta=204.4,219.4
XS Rating Curve= 0 ,0
Exp/Cntr=0.3,0.1

Type RM Length L Ch R = 1 ,332.7   ,100.3,99.7,98.9
XS GIS Cut Line= 3
     1654947.263      229235.127     1655277.231      229401.778
     1655532.763      229374.003
#Sta/Elev= 30
      10 1064.28      20 1061.57      30 1059.21      40 1056.98    59.9 1051.36
    69.9 1048.83    79.9 1046.11    89.9 1043.27    99.9 1041.26   109.9 1040.32
   129.9 1040.19   159.9 1039.53   169.8 1038.99   182.3 1038.09   189.8 1037.74
   197.3 1037.81   199.8 1037.83   219.8 1038.66   239.8 1039.14   289.7 1039.82
   319.7 1040.06   369.7 1040.06   458.6 1041.67     518 1043.18   537.7 1043.54
   547.6 1043.82   557.5 1044.23   587.2 1045.01   616.8 1046.03   626.7 1046.75
#Mann= 3 , 0 , 0
      10      .1       0   182.3    .045       0   197.3     .08       0
Bank Sta=182.3,197.3
XS Rating Curve= 0 ,0
Exp/Cntr=0.3,0.1

Type RM Length L Ch R = 1 ,233     ,171.9,163.4,155.1
XS GIS Cut Line= 3
     1654841.717      229299.566     1655107.247      229418.443
       1655496.1      229385.113
#Sta/Elev= 30
      10 1046.28    20.1  1044.5    30.1 1042.07    40.1 1040.09    60.2  1039.1
    80.3 1037.37    90.3 1037.24   120.4 1037.78   150.5 1038.03   170.5 1038.01
   180.6 1038.19   200.6 1037.99   210.7 1037.32   220.7 1035.88   230.7 1033.92
   233.3 1033.63   240.8  1032.8   248.3 1033.59   250.8 1033.86   260.8 1036.19
   270.9 1037.54   290.9 1037.39     341 1038.18     401 1038.87     431 1039.56
   481.1  1040.3   551.1 1041.58   631.2 1043.48   651.2 1044.24   681.2  1045.1
#Mann= 3 , 0 , 0
      10     .08       0   233.3    .045       0   248.3     .08       0
Bank Sta=233.3,248.3
XS Rating Curve= 0 ,0
Exp/Cntr=0.3,0.1

Type RM Length L Ch R = 1 ,69.6    ,48.5,69.6,90.7
XS GIS Cut Line= 4
     1654710.363      229313.205     1654894.054       229500.64
     1655031.206      229529.762     1655514.029      229418.461
#Sta/Elev= 30
    10.1  1061.1    30.3 1051.57    60.6 1037.98    70.7 1034.14    80.8 1032.36
    90.8 1032.14     111 1032.56   171.6  1031.8   222.1 1031.51   262.4 1029.86
   302.5 1029.46   312.5 1028.12   322.5 1026.23     325 1026.06   332.5 1025.56
     340 1026.51   352.6 1028.85   362.6 1030.11   392.6 1031.61   453.2 1033.14
   503.8 1033.02   534.1 1033.27   584.7 1034.84   604.9 1035.98     615 1037.09
   635.2 1038.09   766.7 1040.95   807.1  1040.9   847.6 1042.45   898.1 1043.91
#Mann= 3 , 0 , 0
    10.1     .06       0     325    .045       0     340     .06       0
#XS Ineff= 2 , 0
       0   292.5    1031               0
Permanent Ineff=
       F       F
Bank Sta=325,340
XS Rating Curve= 0 ,0
Exp/Cntr=0.3,0.1

Chan Stop Cuts=-1
Use User Specified Reach Order=0